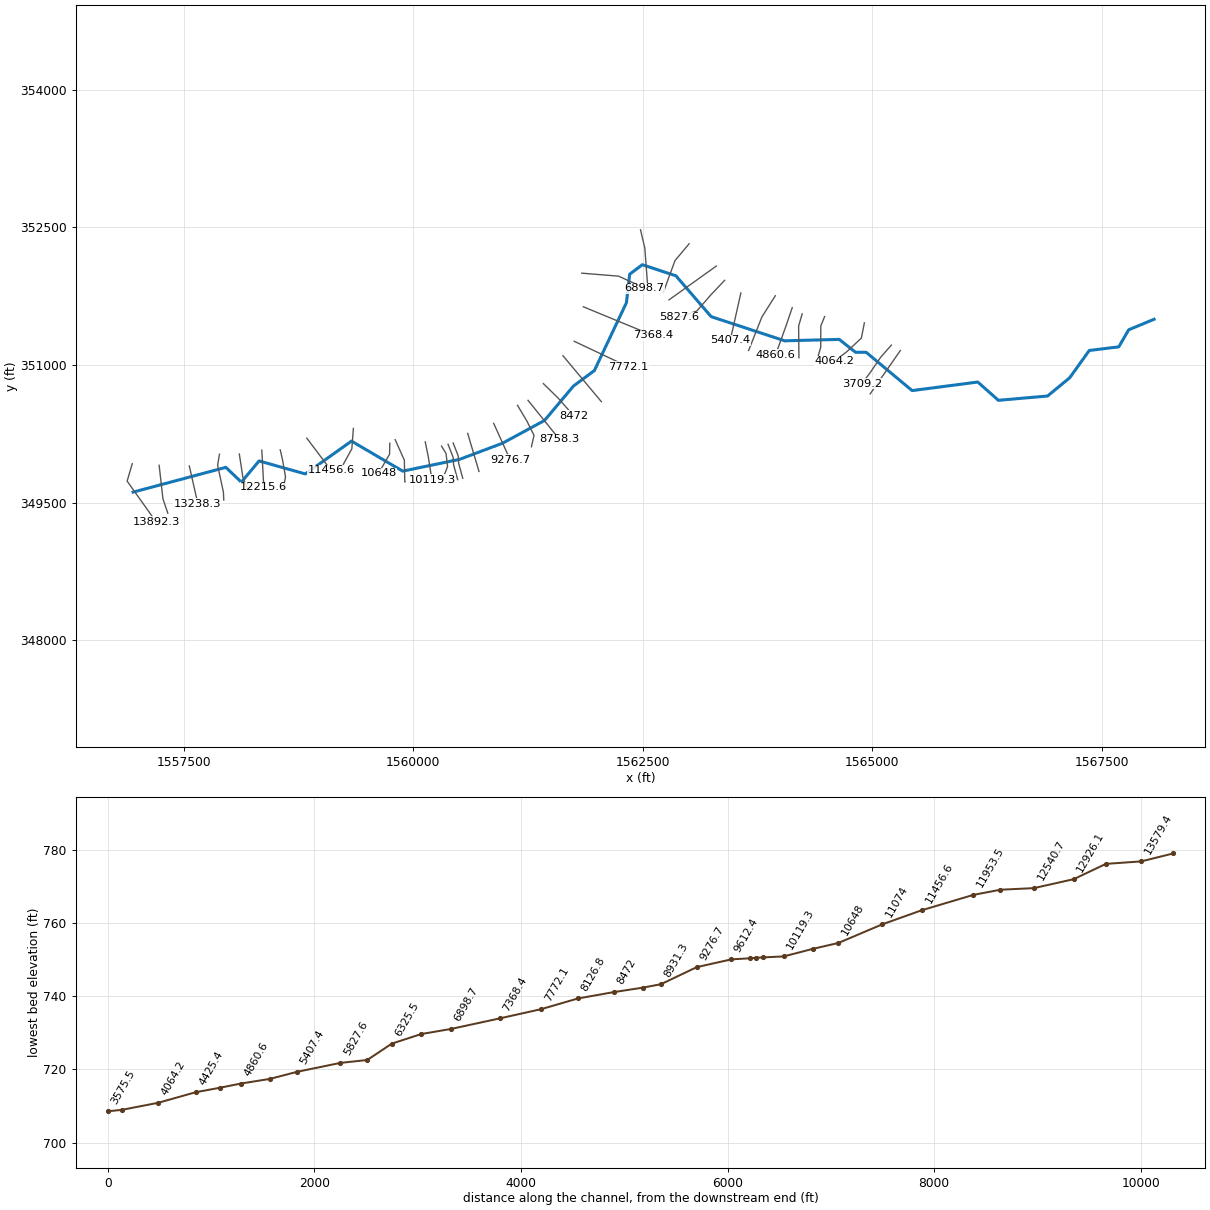
--- LSNCHOCRK.prj (project) ---

Proj Title=LSNCHOCRK
Current Plan=p01
Default Exp/Contr=0,0
English Units
Geom File=g01
Flow File=f01
Plan File=p01
BEGIN DESCRIPTION:
END DESCRIPTION:
DSS Export Rating Curves= 0
DSS Export Rating Curve Sorted= 0
DSS Export Volume Flow Curves= 0
DXF OffsetX= 0
DXF OffsetY= 0
DXF ScaleX= 0
DXF ScaleY= 0

--- LSNCHOCRK.p01 (plan) ---

Plan Title=Floodplain
Program Version=4.00
Geom File=g01
Flow File=f01
K Sum by GR=0
Std Step Tol=0.01
Critical Tol=0.01
Num of Std Step Trials=20
Max Error Tol=0.3
Flow Tol Ratio=0.001
Split Flow NTrial=30
Split Flow Tol=0.02
Split Flow Ratio=0.02
Log Output Level=0
Friction Slope Method=1
Unsteady Friction Slope Method=2
Unsteady Bridges Friction Slope Method=1
Global Log Level=0
CheckData=False
Run HTab=0
Run UNet=0
Run PostProcess=0
UNET Theta=0
UNET Theta Warmup=0
UNET ZTol=0
UNET ZSATol=0
UNET MxIter=0
UNET MaxInSteps=0
UNET DtIC=0
UNET DtMin=0
UNET MaxCRTS=0
UNET WFStab=0
UNET SFStab=0
UNET WFX=0
UNET SFX=0
UNET DSS MLevel=0
UNET DZMax Abort=0
UNET Convert EG Bridges=0
UNET Use Existing IB Tables=0
UNET Froude Limit=0
UNET Froude Power=0
Write IC File=0
Echo Input=False
Echo Output=False
Write Detailed=0

--- LSNCHOCRK.f01 (steady flow) ---

Flow Title=NFF Regression Equation
Program Version=4.10
Number of Profiles= 1
Profile Names=P100yr
River Rch & RM=LSNCHOCRK,Main            ,13892.3
    1084
River Rch & RM=LSNCHOCRK,Main            ,10400.1
    1152
River Rch & RM=LSNCHOCRK,Main            ,10119.3
    1305
River Rch & RM=LSNCHOCRK,Main            ,7772.1
    1423
River Rch & RM=LSNCHOCRK,Main            ,6325.5
    1568
River Rch & RM=LSNCHOCRK,Main            ,4860.6
    1647
River Rch & RM=LSNCHOCRK,Main            ,587.5
    1761
Boundary for River Rch & Prof#=LSNCHOCRK,Main            , 1
Up Type= 0
Dn Type= 3
Dn Slope=0.0064
DSS Import GetInterval= 0
DSS Import GetPeak= 0
DSS Import FillOption= 0

--- LSNCHOCRK.g01 (geometry) ---

Geom Title=USGS 10m DEM
Program Version=4.10

River Reach=LSNCHOCRK       ,Main
Reach XY= 30
     1556948.031      349613.299     1557958.726      349883.537
     1558127.581       349722.33     1558320.715      349953.349
     1558824.336      349811.833     1559327.515       350169.39
     1559885.372      349842.346     1560502.907      349969.863
     1560970.962      350145.211     1561430.249      350393.821
     1561746.164      350769.367     1561974.049      350938.192
     1562323.308      351677.408      1562358.53      351987.784
     1562496.697      352091.556     1562862.669      351970.376
     1563246.263      351525.758     1564048.245      351262.193
     1564641.767      351277.718     1564819.802      351136.965
     1564935.226      351137.264     1565436.226      350719.924
     1566151.531      350813.117     1566376.161      350613.937
     1566912.498      350660.921     1567153.876      350860.438
     1567366.341      351156.978     1567687.931      351196.411
     1567795.834      351382.442     1568072.406      351497.015

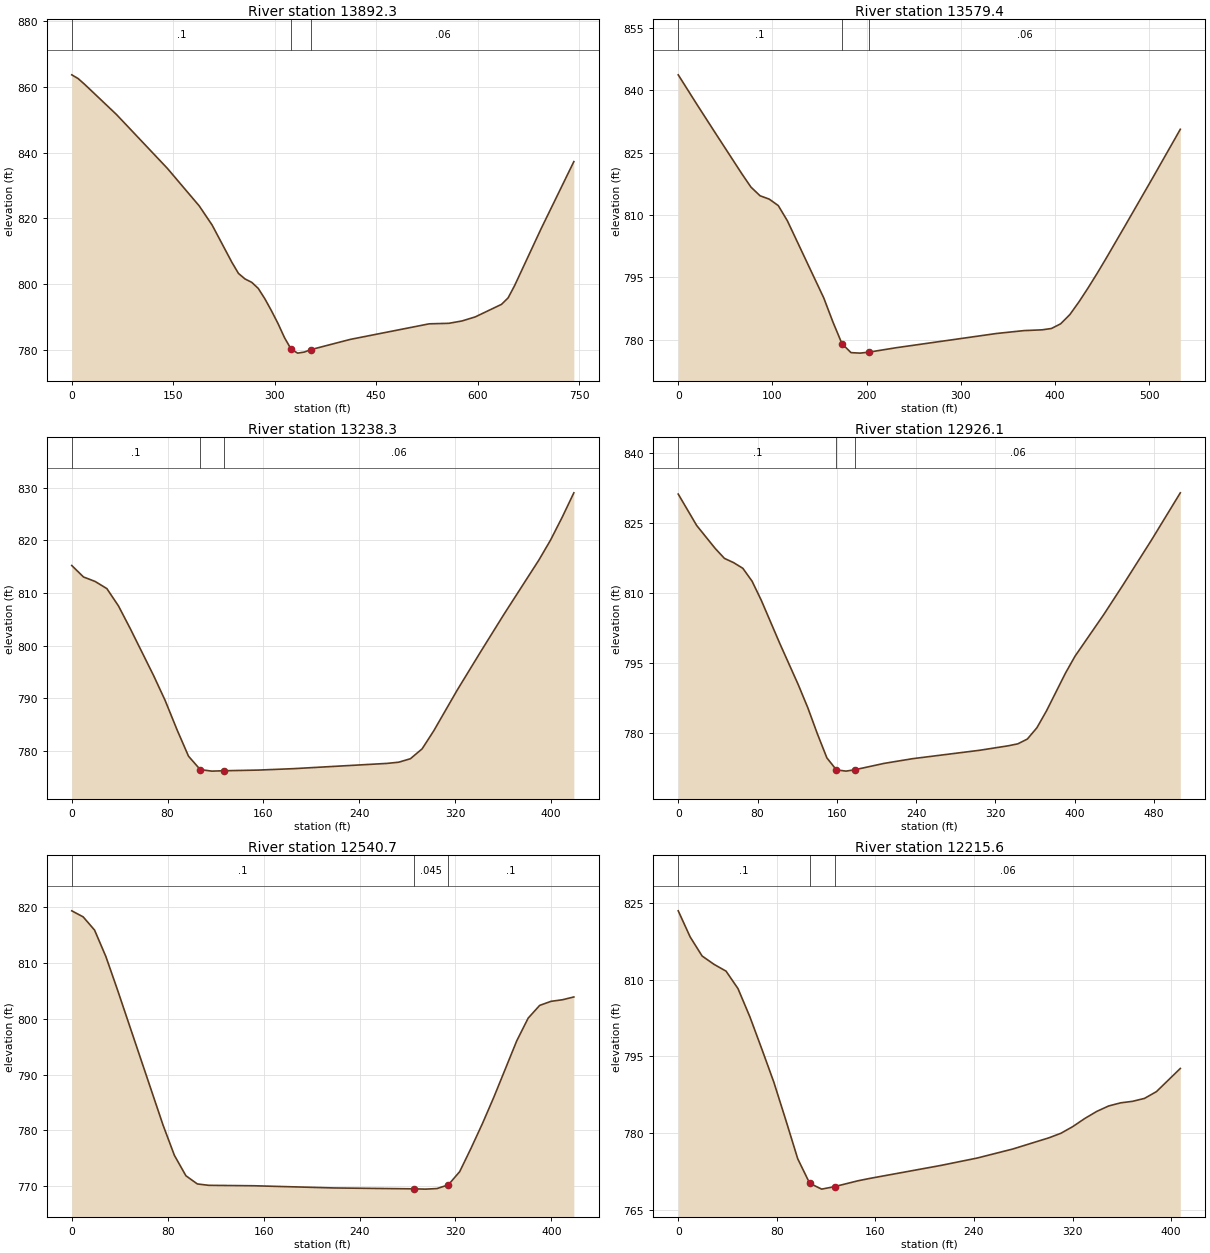
Type RM Length L Ch R = 1 ,13892.3 ,326.5,312.9,298.6
XS GIS Cut Line= 3
     1556938.931      349923.431     1556883.155      349733.548
     1557198.396      349289.526
#Sta/Elev= 30
       0  863.72     9.4  862.58    18.8  860.87      66  851.66   141.4  835.23
   188.5   823.8   207.6  817.96   236.8  806.62   246.5  803.25   256.2  801.56
     266  800.55   275.7   798.7   285.4  795.57   295.2  791.91   304.9  788.02
   314.6  783.68   324.3   780.2     334  778.98   343.8   779.3   353.5  780.04
   411.8  783.16   528.5   787.9   557.7  788.06   577.1  788.78   596.6  790.01
   635.5  793.84   645.2   795.8   654.9  799.58   693.8  816.78   742.4  837.29
#Mann= 3 , 0 , 0
       0      .1       0   324.3    .045       0   353.5     .06       0
Bank Sta=324.3,353.5
XS Rating Curve= 0 ,0
Exp/Cntr=0.3,0.1

Type RM Length L Ch R = 1 ,13579.4 ,338.1,341.1,344.1
XS GIS Cut Line= 3
     1557231.899       349906.07     1557273.132      349541.486
       1557326.3      349384.151
#Sta/Elev= 29
       0  843.68    19.3  836.76    38.6  829.98    67.6  819.88    77.2   816.7
    86.9  814.61    96.6  813.81   106.2  812.26   115.9  808.59   154.5  790.06
   164.1  784.35   173.8  779.08   183.4  776.92   193.1   776.8   202.8  777.05
   231.7  778.11   337.9  781.52   366.9  782.21   386.4   782.4   396.2  782.72
     406  783.85   415.8  786.08   425.5  789.15   435.3  792.54   445.1  796.11
   454.8  799.79   474.4  807.42   503.7  818.93     533  830.59
#Mann= 3 , 0 , 0
       0      .1       0   173.8    .045       0   202.8     .06       0
Bank Sta=173.8,202.8
XS Rating Curve= 0 ,0
Exp/Cntr=0.3,0.1

Type RM Length L Ch R = 1 ,13238.3 ,311.9,312.2,311.8
XS GIS Cut Line= 2
     1557560.675      349898.474     1557652.906      349489.403
#Sta/Elev= 27
       0  815.24     9.8  813.06    19.5  812.21    29.3  810.85      39  807.55
    48.8  803.26    68.3  794.32      78  789.56    87.8  784.05    97.5  778.96
   107.3  776.41     117  776.12   126.8  776.19     156  776.32   185.3  776.59
   263.3  777.59   273.1  777.82   282.8  778.48   292.6  780.36   302.3  783.79
   321.8   791.5   341.3  798.77   360.8  805.91   390.1  816.28   399.8  820.06
   409.6  824.44   419.3  829.07
#Mann= 3 , 0 , 0
       0      .1       0   107.3    .045       0   126.8     .06       0
Bank Sta=107.3,126.8
XS Rating Curve= 0 ,0
Exp/Cntr=0.3,0.1

Type RM Length L Ch R = 1 ,12926.1 ,380.3,385.4,388.6
XS GIS Cut Line= 4
     1557889.451      350026.512     1557868.835      349907.155
     1557931.769      349615.271     1557936.109      349528.465
#Sta/Elev= 30
       0  831.21    18.6   824.5    37.3  819.58    46.6  817.46    55.9  816.54
    65.2  815.33    74.5  812.58    83.9  808.44   102.5  799.24   121.1  790.44
   130.8  785.47   140.4  779.92     150  774.77   159.6  772.21   169.3  771.94
   178.3  772.24   207.8   773.6   236.7  774.61   304.1   776.4     333  777.36
   342.7  777.78   352.3  778.81   361.9  781.22   371.6  784.84   390.8  792.94
   400.4  796.54   429.4  805.45   448.7  811.74   477.7  821.44   506.6  831.48
#Mann= 3 , 0 , 0
       0      .1       0   159.6    .045       0   178.3     .06       0
Bank Sta=159.6,178.3
XS Rating Curve= 0 ,0
Exp/Cntr=0.3,0.1

Type RM Length L Ch R = 1 ,12540.7 ,332.6,325.1,316.1
XS GIS Cut Line= 3
      1558105.38      350028.682     1558144.443      349774.776
     1558203.036      349623.952
#Sta/Elev= 26
       0  819.29     9.5  818.21      19  815.85    28.5  811.08    38.1  805.17
    76.1  780.97    85.6  775.54    95.2  771.89   104.7  770.43   114.2  770.18
   152.2   770.1   218.8  769.71   285.4  769.55     295   769.5   304.5   769.6
     314  770.26   323.5  772.63     333  776.83   342.6  781.29   352.1  786.01
   371.1  796.04   380.6  800.09   390.2  802.37   399.7   803.1   409.2  803.38
   418.7  803.88
#Mann= 3 , 0 , 0
       0      .1       0   285.4    .045       0     314      .1       0
Bank Sta=285.4,314
XS Rating Curve= 0 ,0
Exp/Cntr=0.3,0.1

Type RM Length L Ch R = 1 ,12215.6 ,258.3,262.1,265.3
XS GIS Cut Line= 2
     1558350.606         350071.     1558372.307      349664.099
#Sta/Elev= 30
       0  823.42     9.7  818.31    19.4  814.59    29.1  812.96    38.8  811.64
    48.5  808.23    58.2  802.69    67.9  796.39    77.6  789.95    87.3  782.56
      97  774.98   106.7   770.2   116.4  769.06   126.9  769.55   145.5  770.67
   155.2  771.14   213.4   773.7   242.6  775.13   271.6   776.9   300.8  779.08
   310.5  779.96   320.2  781.27   329.9  782.85   339.6  784.23   349.3   785.3
     359  785.91   368.7  786.21   378.4  786.78   388.1   788.1   407.5  792.63
#Mann= 3 , 0 , 0
       0      .1       0   106.7    .045       0   126.9     .06       0
Bank Sta=106.7,126.9
XS Rating Curve= 0 ,0
Exp/Cntr=0.3,0.1

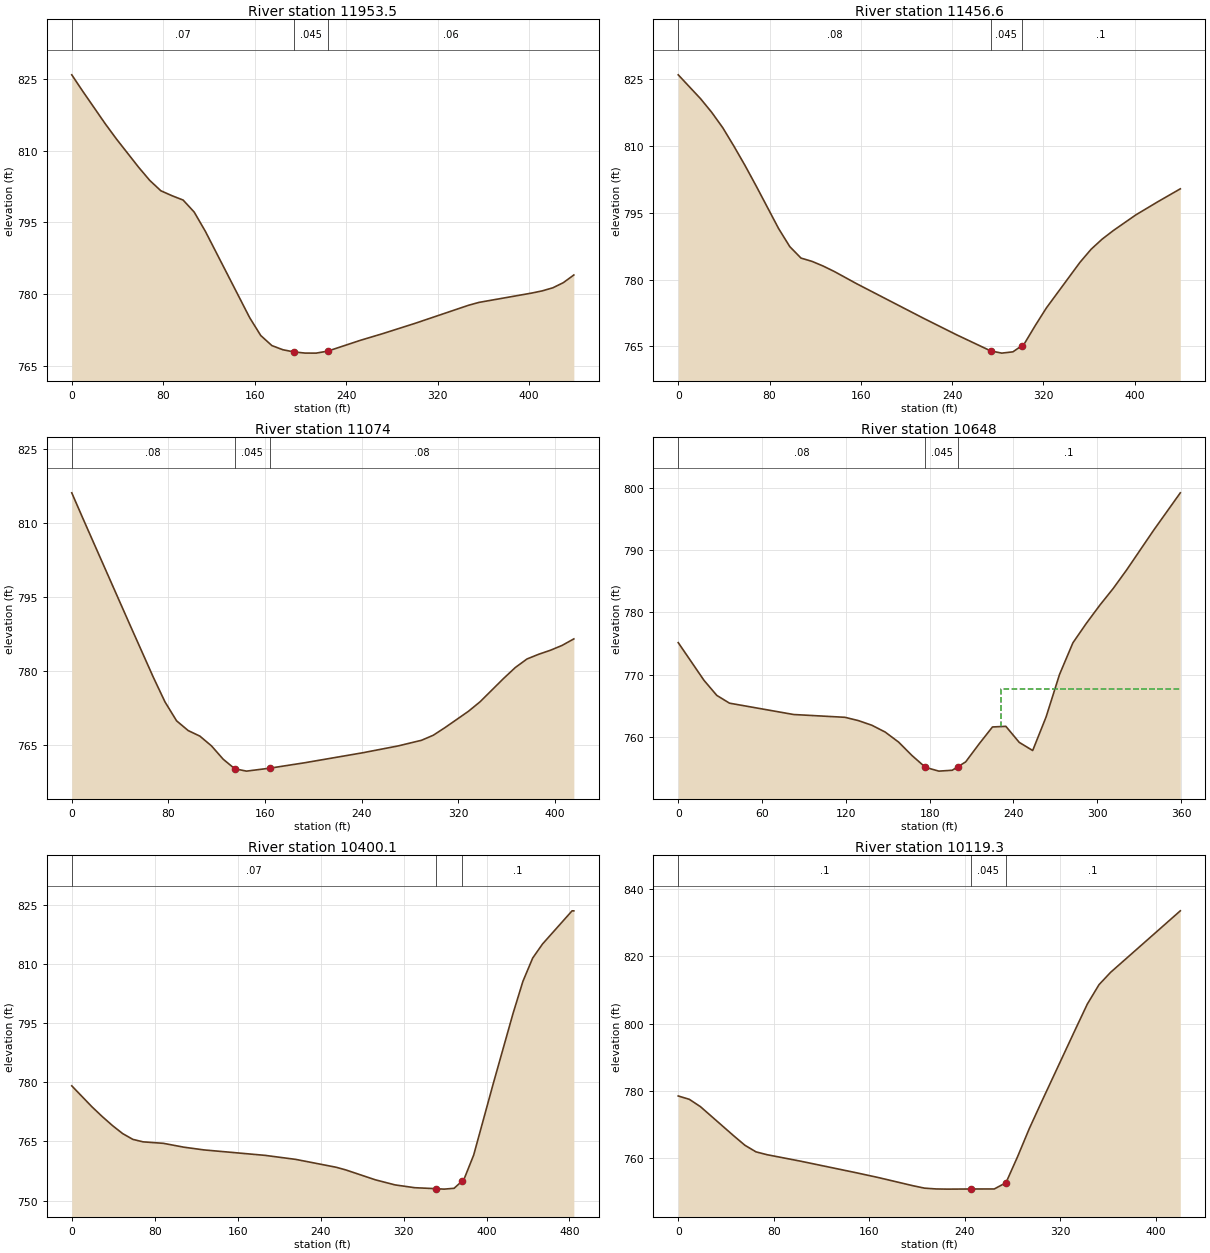
Type RM Length L Ch R = 1 ,11953.5 ,482.9,496.9,509.5
XS GIS Cut Line= 4
     1558551.344      350074.255     1558577.385      349960.323
     1558608.852      349779.116     1558581.726      349643.483
#Sta/Elev= 29
       0   825.9     9.7  822.43    29.2  815.68      39  812.49    58.4  806.57
    68.2   803.8    77.9  801.63    87.6   800.6    97.4  799.68   107.1  797.16
   116.9  793.11   155.6  775.06   165.3  771.32     175  769.22   184.6  768.35
   194.3  767.89     204  767.65   213.7  767.64   223.9  768.06   252.4  770.32
   271.8  771.71   300.8  773.92   346.9  777.65   356.1  778.26   402.2  780.21
   411.4  780.67   420.7  781.31   429.9  782.39   439.1     784
#Mann= 3 , 0 , 0
       0     .07       0   194.3    .045       0   223.9     .06       0
Bank Sta=194.3,223.9
XS Rating Curve= 0 ,0
Exp/Cntr=0.3,0.1

Type RM Length L Ch R = 1 ,11456.6 ,402.6,382.6,362.4
XS GIS Cut Line= 2
     1558841.057      350201.208     1559105.814      349849.646
#Sta/Elev= 30
       0  826.04    19.6  820.66    29.3  817.62    39.1  814.12    48.9  809.96
    58.7  805.59    68.5  800.96      88  791.47    97.8  787.41   107.6  784.84
   117.4  784.09   127.1  783.04   136.9  781.81   156.5  779.06   215.2  771.28
   244.5  767.53   273.8  763.98   283.6  763.47   293.4  763.76   301.4  765.18
   303.2   765.5     313  769.69   322.7  773.63   352.1  783.87   361.9  786.82
   371.6   789.1   381.4  791.03     401  794.53   420.5  797.52   440.1  800.41
#Mann= 3 , 0 , 0
       0     .08       0   273.8    .045       0   301.4      .1       0
Bank Sta=273.8,301.4
XS Rating Curve= 0 ,0
Exp/Cntr=0.3,0.1

Type RM Length L Ch R = 1 ,11074   ,437.8,426,413.1
XS GIS Cut Line= 3
     1559348.436      350307.111     1559331.471      350085.932
     1559238.193      349915.835
#Sta/Elev= 28
       0  816.15     9.6  810.74    48.2  789.32    67.5  778.71    77.2  773.68
    86.8  769.84    96.4  767.86   106.1  766.73   115.7  764.75   125.4  762.04
     135   760.1   144.7  759.62     164  760.22   192.9  761.32   241.2  763.36
   270.3  764.74   289.7  765.89   299.4  766.91   309.1  768.46   328.5  771.77
   338.2  773.72   357.6  778.44   367.3  780.66     377   782.4   386.7  783.36
   396.4  784.17   406.1  785.16   415.8  786.48
#Mann= 3 , 0 , 0
       0     .08       0     135    .045       0     164     .08       0
Bank Sta=135,164
XS Rating Curve= 0 ,0
Exp/Cntr=0.3,0.1

Type RM Length L Ch R = 1 ,10648   ,232.8,247.9,262.8
XS GIS Cut Line= 3
      1559744.92      350146.955      1559742.75      350027.597
     1559623.392      349819.264
#Sta/Elev= 30
       0  775.15    18.4  769.11    27.6  766.68    36.7  765.43    82.6  763.61
   119.4  763.16     129  762.63   138.6  761.89   148.2  760.79   157.8  759.18
   167.4  757.02     177  755.13   186.6  754.52   196.2  754.66   200.2  755.22
   205.8     756   215.4  758.88     225  761.61   234.6  761.71   244.2  759.13
   253.8  757.83   263.4  763.22     273  770.03   282.6  775.12   292.2  778.24
   301.8  781.14   311.5  783.86   321.1  786.83   340.3  793.16   359.5   799.2
#Mann= 3 , 0 , 0
       0     .08       0     177    .045       0   200.2      .1       0
#XS Ineff= 2 , 0
                          231.44          767.67
Permanent Ineff=
       F       F
Bank Sta=177,200.2
XS Rating Curve= 0 ,0
Exp/Cntr=0.3,0.1

Type RM Length L Ch R = 1 ,10400.1 ,276.6,280.8,284.3
XS GIS Cut Line= 4
     1559803.297      350185.583     1559903.715      349961.637
     1559908.332      349724.646     1559910.068      349724.646
#Sta/Elev= 30
       0   779.1    19.6  773.75    29.4  771.31    39.3  769.02    49.1  766.99
    58.9  765.53    68.7   764.9    88.4  764.52     108  763.55   127.6  762.85
   186.5  761.47     216  760.45   254.9  758.46   264.4  757.77   292.8  755.27
   311.8  753.98   330.8  753.27   351.5  753.02   359.2  752.91   368.7  753.12
   376.5  754.96   378.2  755.36   387.6  761.55   406.6  779.78   425.6  797.49
   435.1  805.61   444.5   811.5     454  815.07   482.5  823.48   484.2  823.47
#Mann= 3 , 0 , 0
       0     .07       0   351.5    .045       0   376.5      .1       0
Bank Sta=351.5,376.5
XS Rating Curve= 0 ,0
Exp/Cntr=0.3,0.1

Type RM Length L Ch R = 1 ,10119.3 ,199.7,198.5,196.9
XS GIS Cut Line= 3
     1560131.422      350161.278     1560164.408      349997.215
     1560204.339      349747.215
#Sta/Elev= 26
       0  778.54     9.3  777.54    18.6  775.36    46.5  766.69    55.8   763.9
    65.1  761.93    74.4  761.08   102.3  759.17   148.8  755.74   167.4  754.31
   196.6  751.86   206.3  751.14     216   750.9   225.8  750.85   245.2  750.89
   264.7   750.9   274.1  752.68   274.5  752.76   284.2  760.49   293.9  768.74
   303.7  776.34   332.9  798.55   342.6  805.84   352.4  811.61   362.1  815.28
   420.5  833.57
#Mann= 3 , 0 , 0
       0      .1       0   245.2    .045       0   274.1      .1       0
Bank Sta=245.2,274.1
XS Rating Curve= 0 ,0
Exp/Cntr=0.3,0.1

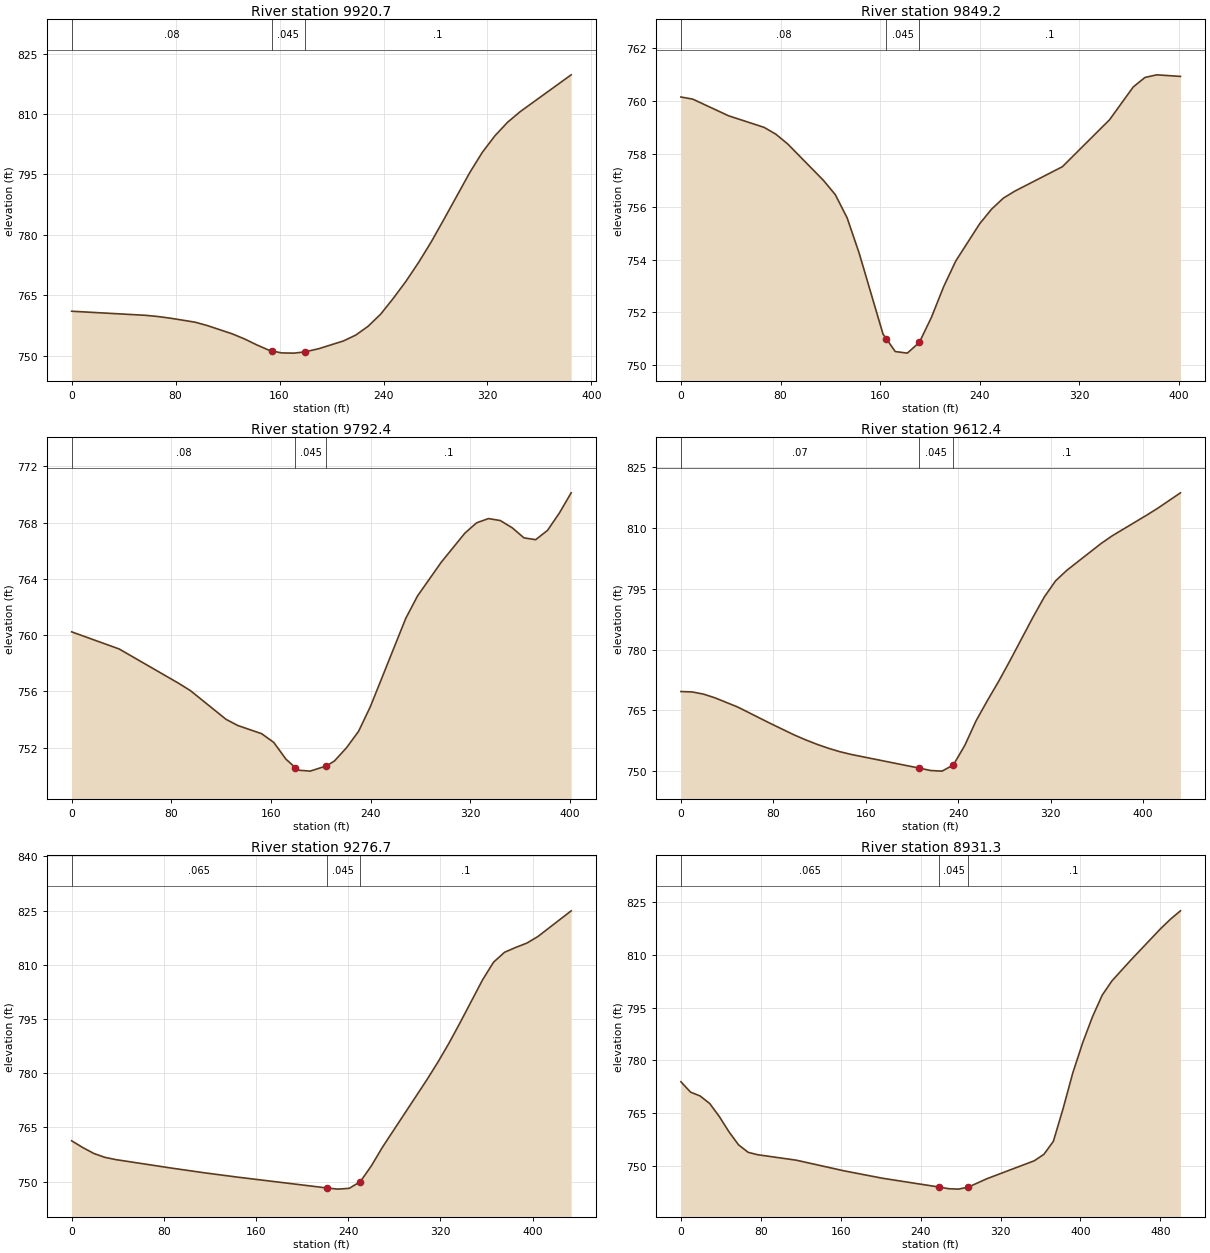
Type RM Length L Ch R = 1 ,9920.7  ,72.2,71.5,70.2
XS GIS Cut Line= 4
     1560308.885      350115.096     1560357.956      350033.791
      1560374.52      349891.961     1560320.603      349755.558
#Sta/Elev= 30
       0     761      57  759.98    66.5  759.68      76  759.27      95  758.28
   104.5  757.43   123.5  755.39     133  754.12   142.6  752.62   152.1  751.28
   154.3  751.13   161.6  750.64   171.1  750.59   179.3  750.89   190.2  751.69
   209.2  753.62   218.7  755.08   228.2  757.28   237.8  760.27   247.5  764.19
   257.3  768.45   267.1  773.17   276.9  778.32   286.6  783.89   306.2  795.35
     316  800.46   325.8  804.61   335.5  807.96   345.3  810.61   384.4  819.73
#Mann= 3 , 0 , 0
       0     .08       0   154.3    .045       0   179.3      .1       0
Bank Sta=154.3,179.3
XS Rating Curve= 0 ,0
Exp/Cntr=0.3,0.1

Type RM Length L Ch R = 1 ,9849.2  ,57.7,56.8,56.6
XS GIS Cut Line= 4
      1560379.87      350134.459     1560435.223      349992.242
     1560439.563      349914.551     1560484.282      349749.863
#Sta/Elev= 28
       0  760.16     9.5  760.08    38.2  759.45    66.8  759.01    76.3  758.75
    85.8  758.38   114.5     757     124  756.46   133.5  755.58   143.1  754.25
   162.3  751.18     165     751   172.1  750.52   181.8  750.46   191.5  750.87
   201.2  751.82     211  752.98   220.7  753.95   239.9  755.36   249.4  755.91
   258.9  756.33   268.3   756.6   306.3  757.52   344.2   759.3   363.2  760.54
   372.6   760.9   382.1     761   401.1  760.94
#Mann= 3 , 0 , 0
       0     .08       0     165    .045       0   191.5      .1       0
Bank Sta=165,191.5
XS Rating Curve= 0 ,0
Exp/Cntr=0.3,0.1

Type RM Length L Ch R = 1 ,9792.4  ,173.4,180,186.4
XS GIS Cut Line= 4
     1560435.425      350149.042     1560490.778      350006.826
     1560495.119      349929.135     1560539.838      349764.446
#Sta/Elev= 30
       0  760.24    38.2  759.02    85.8  756.59    95.4  756.06     124  754.02
   133.5  753.58   152.6     753   162.3  752.38   172.1  751.19   179.6  750.59
   181.8  750.41   191.5  750.34   204.6  750.71     211  751.06   220.7     752
   230.4  753.17   239.9  754.93   268.3   761.2   277.8   762.8   296.8  765.19
   315.8  767.26   325.2  767.99   334.7  768.29   344.2  768.15   353.7  767.64
   363.2  766.92   372.6  766.79   382.1  767.45   391.6  768.68   401.1  770.12
#Mann= 3 , 0 , 0
       0     .08       0   179.6    .045       0   204.6      .1       0
Bank Sta=179.6,204.6
XS Rating Curve= 0 ,0
Exp/Cntr=0.3,0.1

Type RM Length L Ch R = 1 ,9612.4  ,331.9,335.7,339.4
XS GIS Cut Line= 4
     1560593.718      350253.355     1560593.718      350253.355
     1560716.716      349838.826     1560716.716      349838.826
#Sta/Elev= 30
       0  769.66     9.8  769.56    19.6  769.02    29.5  768.11    49.1  765.85
    78.6  761.64    98.3  758.94   108.1  757.74   117.9  756.65   127.8  755.67
   137.6  754.84   147.4  754.16   206.4  750.79   216.2   750.2     226  750.05
   235.8  751.56   245.7  756.37   255.5  762.45   265.3  767.44   275.2  772.25
     285  777.35   304.6  787.89   314.5  792.93   324.3  796.93   334.1  799.54
   363.6  806.11   373.4  808.04   402.9  813.07   412.7  814.81   432.4  818.62
#Mann= 3 , 0 , 0
       0     .07       0   206.4    .045       0   235.8      .1       0
Bank Sta=206.4,235.8
XS Rating Curve= 0 ,0
Exp/Cntr=0.3,0.1

Type RM Length L Ch R = 1 ,9276.7  ,344.1,345.4,346.2
XS GIS Cut Line= 2
     1560876.741      350363.207     1561055.551      349968.258
#Sta/Elev= 26
       0   761.3     9.6  759.44    19.3  757.78    28.9  756.71    38.5  756.08
    86.7  753.74   115.6  752.42   144.5  751.22   221.6  748.24   231.2  747.92
   240.9  748.14   249.9  749.86   250.5  749.98   260.1  754.36   269.8  759.56
   308.3  778.19   317.9  783.08   327.6  788.39   337.2  794.04   356.5  805.77
   366.1  810.71   375.7  813.47   385.4  814.81     395     816   404.6  817.82
   433.5  824.94
#Mann= 3 , 0 , 0
       0    .065       0   221.6    .045       0   249.9      .1       0
Bank Sta=221.6,249.9
XS Rating Curve= 0 ,0
Exp/Cntr=0.3,0.1

Type RM Length L Ch R = 1 ,8931.3  ,166.9,173,178.7
XS GIS Cut Line= 4
      1561136.63      350558.847     1561235.589      350393.917
     1561316.318      350232.458      1561288.54      350108.327
#Sta/Elev= 30
       0  773.86     9.6  770.91    19.2  769.81    28.8  767.67    38.5  763.93
    48.1  759.61    57.7  755.89    67.3  753.76    76.9  753.07   115.4  751.52
   163.5  748.47   201.8  746.37   258.8  743.85   268.4  743.38   277.8  743.27
   287.4  743.81   306.4  746.24   353.8  751.35   363.4  753.18   372.9   756.9
   382.6  766.19   392.4  776.44   402.2  784.94     412  792.34   421.8  798.54
   431.6  802.62   451.1  808.72   480.5  817.54   490.3  820.21   500.1  822.55
#Mann= 3 , 0 , 0
       0    .065       0   258.8    .045       0   287.4      .1       0
Bank Sta=258.8,287.4
XS Rating Curve= 0 ,0
Exp/Cntr=0.3,0.1

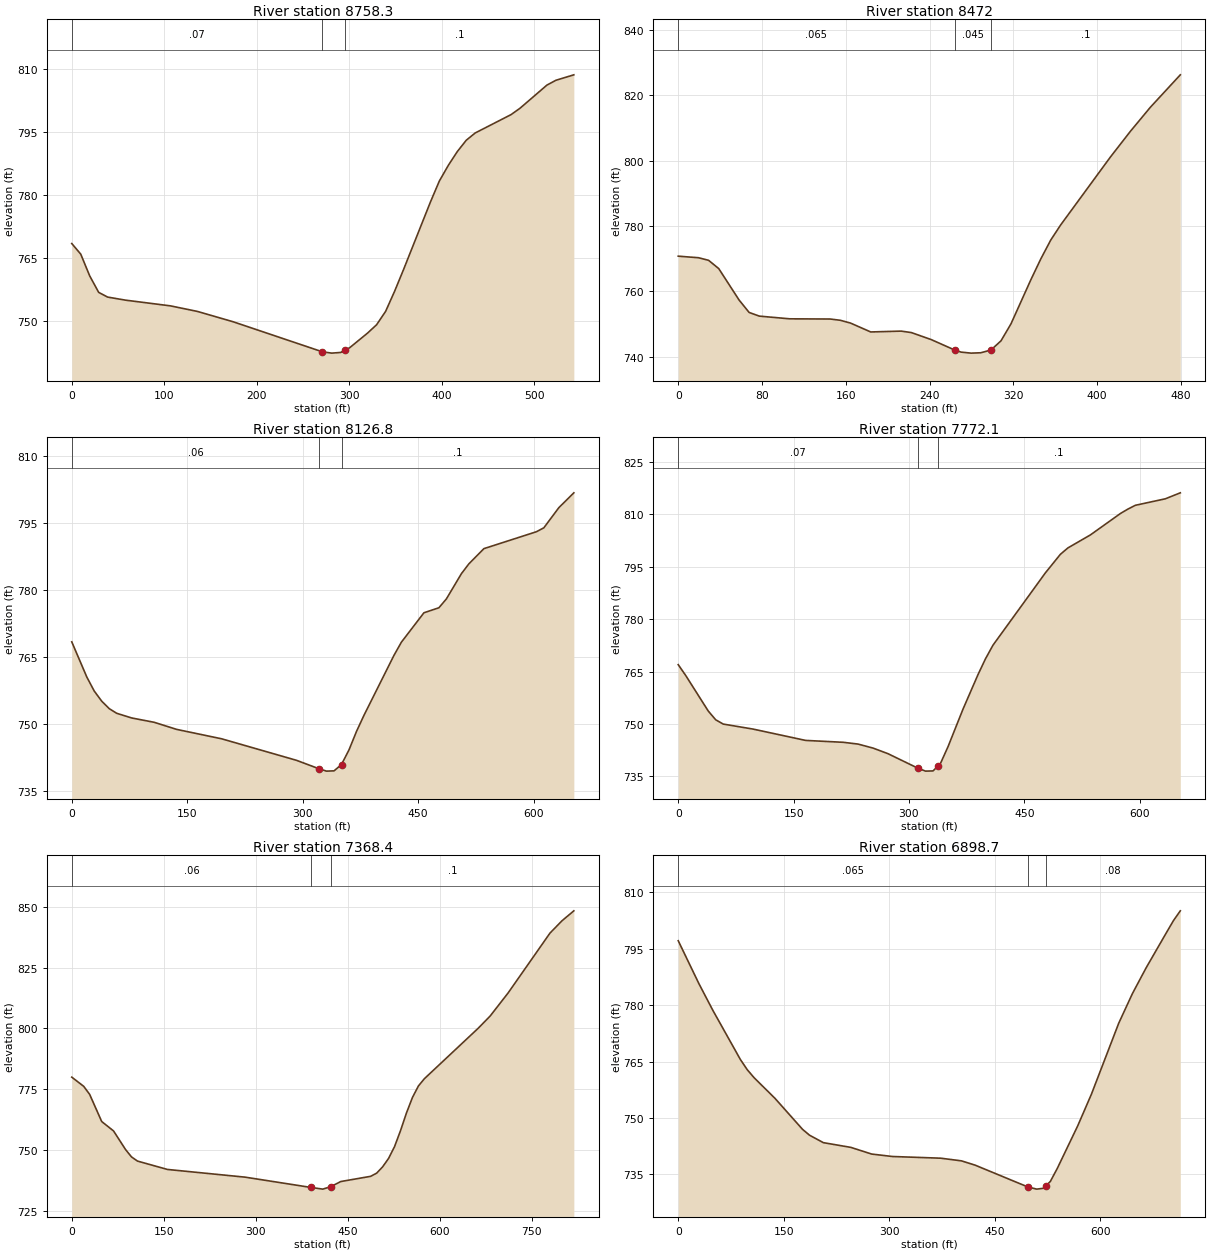
Type RM Length L Ch R = 1 ,8758.3  ,284.2,286.3,287.1
XS GIS Cut Line= 2
     1561251.214      350613.535     1561591.491      350190.792
#Sta/Elev= 30
       0  768.47     9.7  765.94    19.4  760.75    29.1  756.82    38.8   755.7
    58.1  754.97   106.6  753.61   135.7  752.29   174.4  749.82   270.8  742.66
     281  742.34   290.7   742.5   295.8  743.09   300.4  743.63   319.8  747.13
   329.5  749.11   339.2  752.28   348.9  757.05   358.6  762.25   387.6  778.32
   397.3  783.36     407   787.1   416.7  790.38   426.4  793.09   436.1  794.83
   474.8   799.2   484.5  800.72   513.6  806.24   523.3  807.39   542.7  808.69
#Mann= 3 , 0 , 0
       0     .07       0   270.8    .045       0   295.8      .1       0
Bank Sta=270.8,295.8
XS Rating Curve= 0 ,0
Exp/Cntr=0.3,0.1

Type RM Length L Ch R = 1 ,8472    ,345.8,345.2,344
XS GIS Cut Line= 3
     1561418.575      350795.653     1561577.623      350639.985
     1561747.373      350447.291
#Sta/Elev= 30
       0  770.78    19.4   770.3      29  769.51    38.7  766.97    58.1  757.36
    67.7  753.55    77.4  752.43   106.4   751.6   145.1  751.54   154.8  751.15
   164.5   750.3   183.8  747.58   212.9  747.84   222.6  747.39   241.6  745.24
   263.9  742.06   270.1  741.41   279.6   741.1   288.9  741.21   298.6  742.05
   308.2  744.87   317.7  750.05   336.7  763.56   346.2  769.94   355.7  775.72
   365.2  780.36   412.8  801.19   431.8  809.02   450.8  816.36   479.4  826.29
#Mann= 3 , 0 , 0
       0    .065       0   263.9    .045       0   298.6      .1       0
Bank Sta=263.9,298.6
XS Rating Curve= 0 ,0
Exp/Cntr=0.3,0.1

Type RM Length L Ch R = 1 ,8126.8  ,342.5,354.7,366.6
XS GIS Cut Line= 2
     1561631.827      351099.791     1562050.077      350599.154
#Sta/Elev= 30
       0  768.36    19.5  760.49    29.2  757.33      39  755.04    48.7  753.38
    58.4  752.34    77.9  751.29   107.1  750.32   136.3  748.73   194.7  746.62
   292.1  741.79   321.3   739.9     331  739.37   340.8  739.43   350.5  740.85
   360.3  744.16     370  748.28   379.7  751.89   418.7  765.34   428.4  768.31
   457.6  774.88   477.1  776.01   486.8  777.99   506.3  783.65     516  785.85
   535.5  789.26   603.7  793.05   613.4  793.93   632.9  798.45   652.4  801.78
#Mann= 3 , 0 , 0
       0     .06       0   321.3    .045       0   350.5      .1       0
Bank Sta=321.3,350.5
XS Rating Curve= 0 ,0
Exp/Cntr=0.3,0.1

Type RM Length L Ch R = 1 ,7772.1  ,402.2,403.7,405
XS GIS Cut Line= 2
      1561754.44      351257.126     1562344.718      350978.263
#Sta/Elev= 30
       0  766.96     9.7  763.87      39  753.69    48.7  751.17    58.5  749.94
    97.4   748.5   165.6  745.26   214.4  744.72   233.8  744.21   253.3  743.06
   272.8  741.45   311.8  737.28   321.6  736.46   331.3  736.52   337.5   737.9
     341  738.68   350.8  743.47   370.3  754.24   389.8  764.13   399.5  768.64
   409.2  772.53   477.4  793.27   496.9  798.58   506.7  800.41   535.9  804.13
   574.9  810.26   584.6  811.52   594.4  812.62   633.4  814.48   652.8  816.19
#Mann= 3 , 0 , 0
       0     .07       0   311.8    .045       0   337.5      .1       0
Bank Sta=311.8,337.5
XS Rating Curve= 0 ,0
Exp/Cntr=0.3,0.1

Type RM Length L Ch R = 1 ,7368.4  ,470.5,469.8,468.3
XS GIS Cut Line= 2
     1561853.538       351633.05     1562610.745      351320.906
#Sta/Elev= 30
       0  779.95    19.5  776.17    29.2  772.86    48.8  761.72    68.2  757.82
    87.8  750.17    97.5  747.15   107.2  745.45     156  742.01   282.8  738.84
     390  734.62   409.5  733.92   422.6  734.94   438.8  737.04   487.5  739.18
   497.3  740.48     507  743.05   516.8  746.55   526.5  751.38   536.3  757.98
     546  765.25   555.8  771.63   565.5  776.34   575.3  779.33     663  800.05
   682.5  805.08   711.8  814.57     780  839.14   799.5  844.19     819  848.32
#Mann= 3 , 0 , 0
       0     .06       0     390    .045       0   422.6      .1       0
Bank Sta=390,422.6
XS Rating Curve= 0 ,0
Exp/Cntr=0.3,0.1

Type RM Length L Ch R = 1 ,6898.7  ,319.5,289.9,260.8
XS GIS Cut Line= 3
     1561836.905      351999.313     1562238.381      351966.761
     1562520.846      351836.119
#Sta/Elev= 30
       0  797.13    29.5  785.68    49.1  778.66    88.4  765.53    98.2  762.81
   108.1  760.65   137.5  755.22   176.8  746.95   186.7   745.4   206.3  743.42
   245.6  742.15   275.1  740.38   304.6  739.73   373.3  739.28   402.8  738.57
   422.2  737.43   497.3  731.62   509.8  731.05   519.5  731.28   522.3  731.81
   529.2   733.1     539  736.54   568.1  747.88   587.6  756.31   626.5  775.22
   645.9  783.07   665.4  789.93   694.6   799.4   704.3   802.5     714  805.09
#Mann= 3 , 0 , 0
       0    .065       0   497.3    .045       0   522.3     .08       0
Bank Sta=497.3,522.3
XS Rating Curve= 0 ,0
Exp/Cntr=0.3,0.1

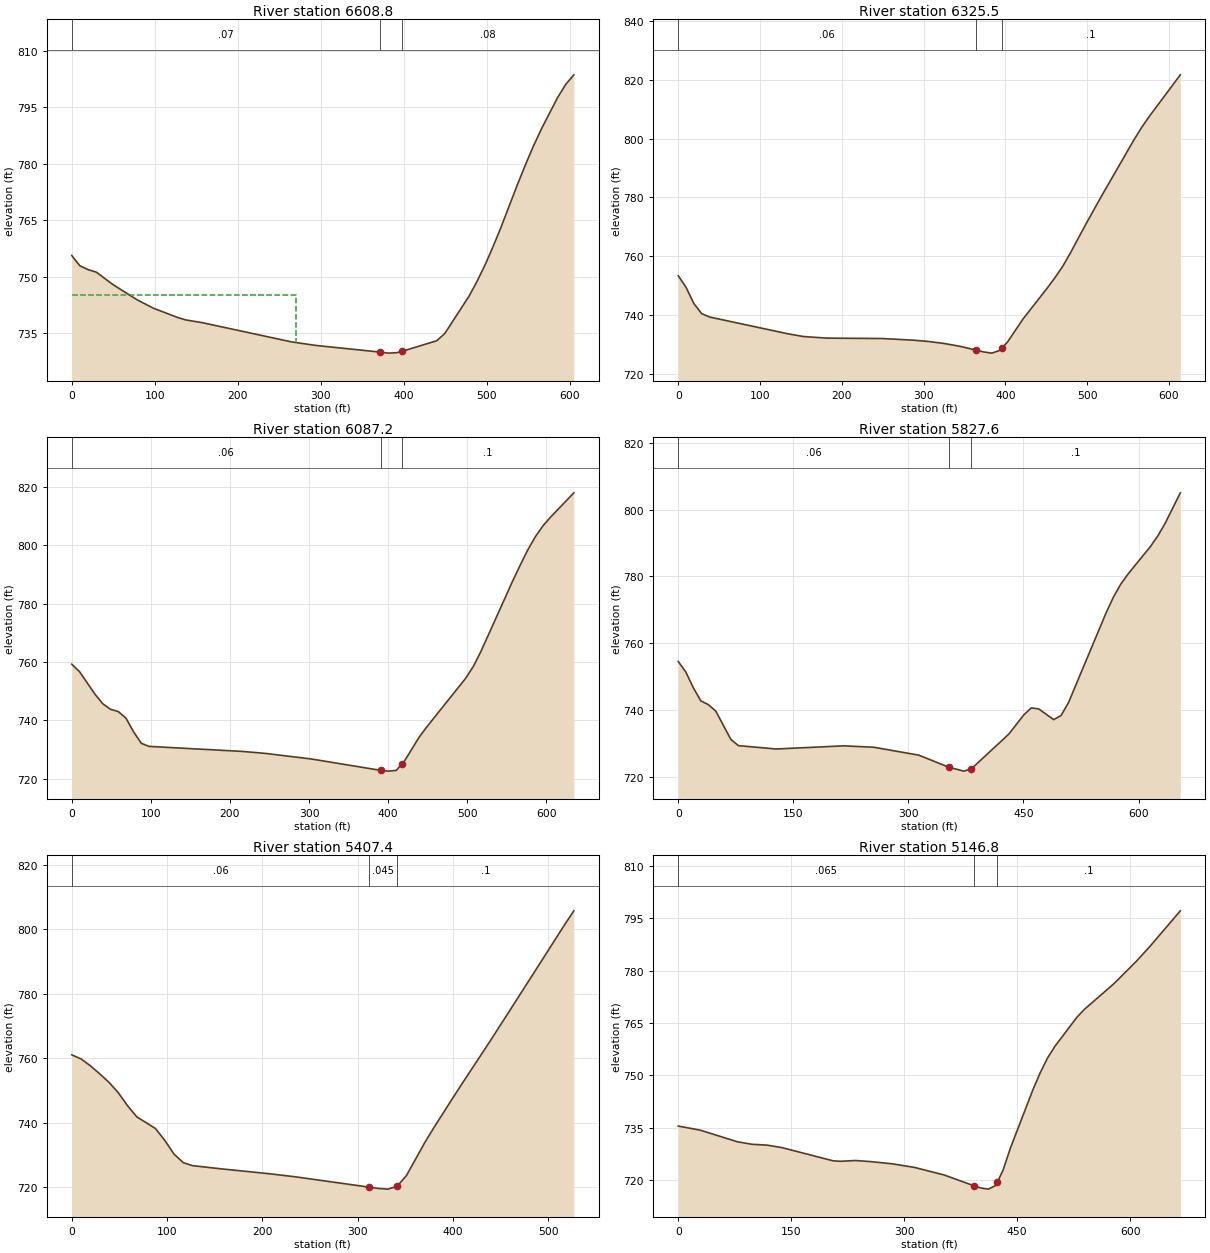
Type RM Length L Ch R = 1 ,6608.8  ,294.3,283.2,270.7
XS GIS Cut Line= 3
     1562477.096      352471.318     1562524.101      352270.147
     1562553.398      351873.011
#Sta/Elev= 30
       0   755.6     9.8  752.87    19.7  751.86    29.5  751.19    49.2  747.94
    78.7  743.83    98.4  741.59   127.9   739.1   137.7  738.46   157.4  737.74
   264.9  732.63     294   731.7   371.7  729.92   381.4  729.65   391.1  729.75
   398.2  730.16   439.7  732.94   449.4  734.89   478.5  744.78   488.2  748.73
     498  753.18   507.7  758.07   517.4  763.31   536.8  774.44   546.5  779.73
   556.2  784.76     566  789.38   585.4  797.68   595.1  801.12   604.8  803.65
#Mann= 3 , 0 , 0
       0     .07       0   371.7    .045       0   398.2     .08       0
#XS Ineff= 2 , 0
          270.68  745.05
Permanent Ineff=
       F       F
Bank Sta=371.7,398.2
XS Rating Curve= 0 ,0
Exp/Cntr=0.3,0.1

Type RM Length L Ch R = 1 ,6325.5  ,254.8,238.4,221.8
XS GIS Cut Line= 3
     1563006.234      352319.553      1562852.53      352136.032
     1562723.407      351784.469
#Sta/Elev= 30
       0  753.36     9.6  749.38    19.2  743.86    28.7  740.46    38.3  739.32
   134.1  733.61   153.2  732.68   181.9  732.14     249  732.01   287.4  731.45
   306.6  730.98   325.8  730.29     345  729.33   364.2  728.06   373.8  727.43
   383.4  727.04     393  727.95   395.8  728.78   402.6  730.81   421.8  738.73
   450.7  748.98   460.3  752.56   469.9  756.46   479.5  761.09   498.7  771.04
   517.9   780.6   556.3  799.12   565.9  803.48   575.5  807.35   613.9  821.66
#Mann= 3 , 0 , 0
       0     .06       0   364.2    .045       0   395.8      .1       0
Bank Sta=364.2,395.8
XS Rating Curve= 0 ,0
Exp/Cntr=0.3,0.1

Type RM Length L Ch R = 1 ,6087.2  ,253.1,259.6,266
XS GIS Cut Line= 2
     1563303.181      352077.004     1562786.688      351708.081
#Sta/Elev= 30
       0  759.23     9.8  756.68    29.3  748.97    39.1   745.7    48.8  743.79
    58.6  743.02    68.4   740.8    78.1  736.06    87.9  732.11    97.6  731.06
   214.8  729.34   244.1  728.67   302.7  726.74   390.6  722.83   400.4  722.57
   410.1  722.82   417.8  725.11   419.9  725.74   439.4  734.32   449.2  737.87
     498  754.42   507.8  758.55   517.5  763.74   556.6  787.31   566.4   792.9
   576.1  798.24   585.9  802.88   595.7  806.69   605.4   809.7   634.7  817.99
#Mann= 3 , 0 , 0
       0     .06       0   390.6    .045       0   417.8      .1       0
Bank Sta=390.6,417.8
XS Rating Curve= 0 ,0
Exp/Cntr=0.3,0.1

Type RM Length L Ch R = 1 ,5827.6  ,405.5,420.2,434.1
XS GIS Cut Line= 4
     1563393.583      351921.324     1563245.169      351764.922
     1563091.009      351587.676     1562899.194      351518.708
#Sta/Elev= 30
       0  754.57     9.8  751.46    19.6  746.75    29.4   742.8    39.2  741.68
      49  739.72    68.6  731.26    78.4  729.41   127.4   728.4   215.6  729.34
   254.8  728.93   313.5  726.56   352.6  722.96   372.2  721.78     382  722.46
   430.9  732.86   450.5  738.62   460.2  740.69   469.9  740.38   489.4  737.18
     499  738.41   508.8  742.34   557.3  768.91     567  773.72   576.7  777.68
   586.4  780.76   615.5  788.96   625.2  792.17   634.9  796.01   654.4  805.01
#Mann= 3 , 0 , 0
       0     .06       0   352.6    .045       0     382      .1       0
Bank Sta=352.6,382
XS Rating Curve= 0 ,0
Exp/Cntr=0.3,0.1

Type RM Length L Ch R = 1 ,5407.4  ,264.7,260.6,256.1
XS GIS Cut Line= 2
     1563570.388      351783.897     1563454.811      351269.851
#Sta/Elev= 29
       0  760.98     9.8  759.72    19.5   757.6    29.3   755.1      39  752.48
    48.8  749.26    58.5  745.22    68.3  741.75    87.8  738.15    97.6  734.47
   107.3   730.2   117.1  727.53   126.8  726.62   156.1  725.65   204.9  724.19
   234.2  723.18   312.2  719.95     322  719.55   331.7  719.34   341.5  720.23
   351.2  723.55   370.8  733.96   380.5  738.63     400  747.67   409.8  752.13
   439.1  765.28   478.1  783.23   517.1  801.29   526.9  805.65
#Mann= 3 , 0 , 0
       0     .06       0   312.2    .045       0   341.5      .1       0
Bank Sta=312.2,341.5
XS Rating Curve= 0 ,0
Exp/Cntr=0.3,0.1

Type RM Length L Ch R = 1 ,5146.8  ,285.3,286.2,287
XS GIS Cut Line= 3
     1563945.542      351753.653     1563799.058      351521.449
     1563654.744      351156.865
#Sta/Elev= 30
       0   735.5    29.4  734.32    78.4     731      98  730.27   117.7  730.04
   137.3  729.34   205.9  725.52   215.7   725.4   235.3  725.62   254.9  725.32
   284.4  724.67   313.8  723.64     353  721.48   392.2  718.41     402  717.74
   411.8  717.42   421.6  718.48   423.6  719.39   431.4  722.94   441.2  729.29
   470.6  745.75   480.4  750.68   490.2  754.97     500  758.32   529.4   766.7
   539.2  768.94   578.4   776.3   607.8  782.62   627.4  787.27   666.6  797.19
#Mann= 3 , 0 , 0
       0    .065       0   392.2    .045       0   423.6      .1       0
Bank Sta=392.2,423.6
XS Rating Curve= 0 ,0
Exp/Cntr=0.3,0.1

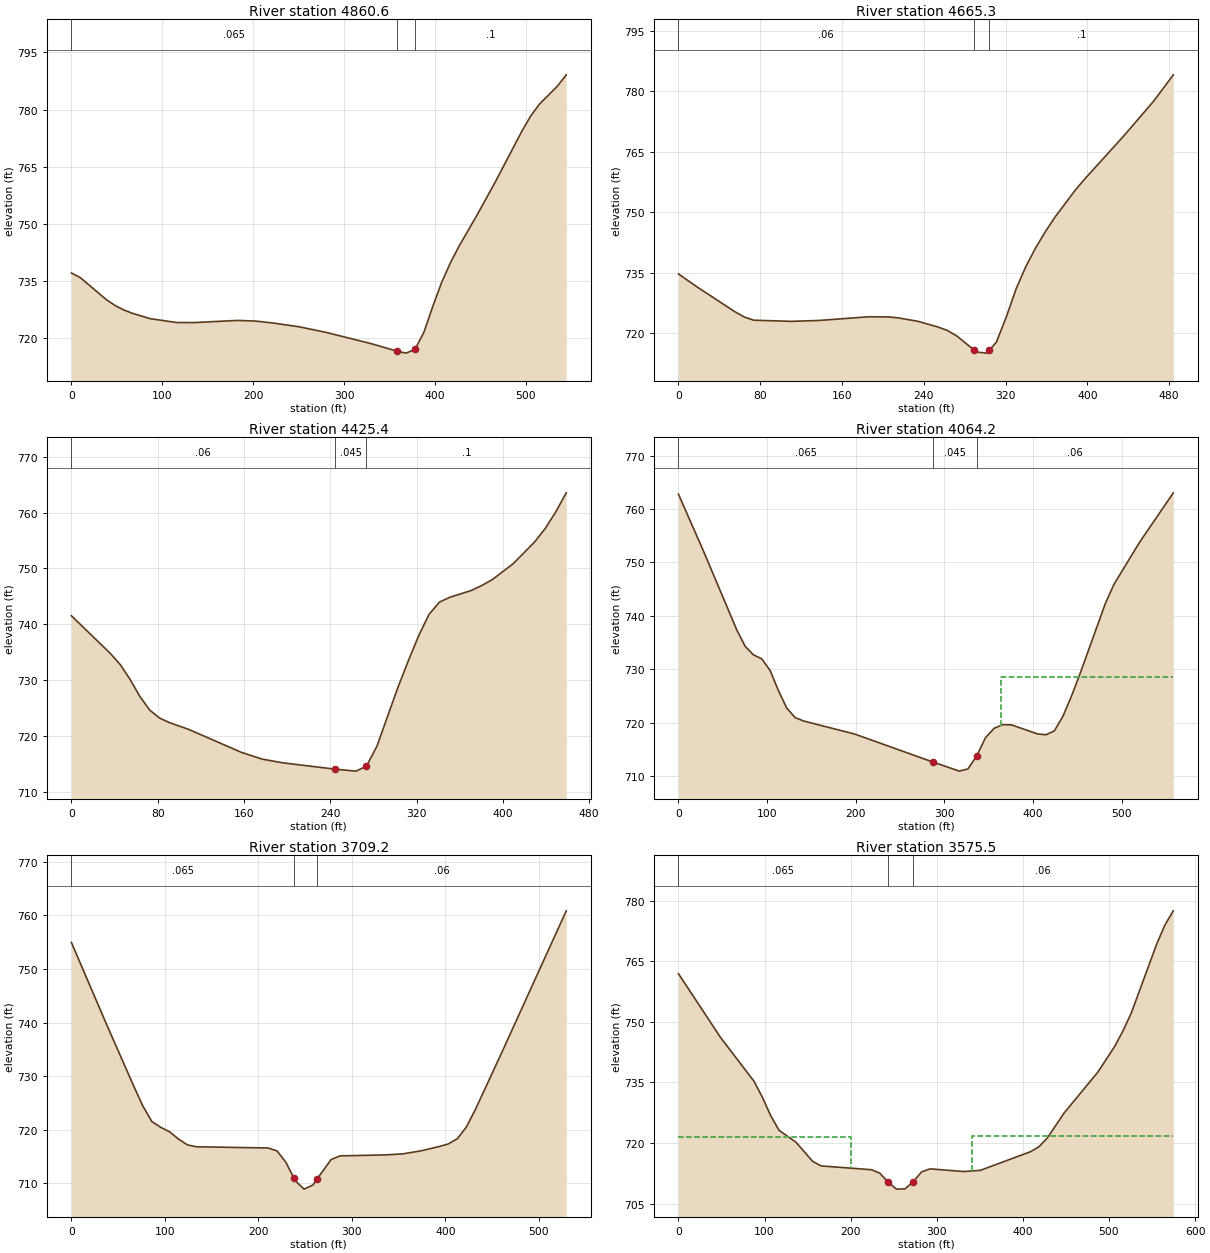
Type RM Length L Ch R = 1 ,4860.6  ,185.2,195.3,204.8
XS GIS Cut Line= 3
     1564130.004      351623.445     1564058.389      351414.027
     1563948.797      351110.207
#Sta/Elev= 30
       0  737.13     9.6  735.95    38.5  730.14    48.1   728.6    57.7  727.43
    67.4  726.54    86.6  725.16   115.5  724.15   134.7  724.13   182.8   724.7
   202.1  724.53   221.3  724.03   250.7  723.02     280  721.57     329  718.65
   358.4  716.63   368.1  716.12   377.9  717.11   387.7  721.57   397.5  728.37
   407.3   734.7   417.1  739.92   426.9  744.38   446.4  752.42     466   760.9
   495.4  774.27   505.2   778.3   514.9  781.44   534.5   786.1   544.3   789.1
#Mann= 3 , 0 , 0
       0    .065       0   358.4    .045       0   377.9      .1       0
Bank Sta=358.4,377.9
XS Rating Curve= 0 ,0
Exp/Cntr=0.3,0.1

Type RM Length L Ch R = 1 ,4665.3  ,240.1,240,239.4
XS GIS Cut Line= 3
     1564238.511      351556.171     1564199.631      351423.804
     1564202.704      351077.655
#Sta/Elev= 30
       0  734.69    18.4  731.43    55.2   725.3    64.4  723.99    73.6   723.2
   110.4  722.91     138  723.14     186  724.05   205.3  724.01   214.9  723.78
   234.1  722.93   253.4  721.55     263  720.66   272.6  719.23   289.2  715.79
   291.8  715.29   301.4  715.02  304.19  715.76     311  717.74   320.7  723.99
   330.3  730.97   339.9  736.56   349.5   741.2   359.1  745.26   368.7  748.92
     388  755.44   397.6  758.31     436  769.07   464.9  777.61   484.1  784.14
#Mann= 3 , 0 , 0
       0     .06       0   289.2    .045       0  304.19      .1       0
Bank Sta=289.2,304.19
XS Rating Curve= 0 ,0
Exp/Cntr=0.3,0.1

Type RM Length L Ch R = 1 ,4425.4  ,383.2,361.2,338
XS GIS Cut Line= 4
     1564482.652      351525.789     1564441.419      351424.877
     1564440.334      351192.673     1564407.782      351079.825
#Sta/Elev= 30
       0  741.54    36.3  734.76    45.4  732.78    54.5  730.12    63.6  727.07
    72.7  724.65    81.8  723.24    90.8  722.44     109   721.2   157.4  717.13
   176.7  715.91   196.1  715.24   244.5  714.11   263.8  713.76   273.5  714.65
   283.2  718.21   302.5  728.64   312.2  733.43   321.9  737.97   331.5  741.79
   341.2  743.98     351  744.86   370.6  746.05   380.4  746.95   390.2  748.01
   409.7  750.88   429.3  754.72   439.1  757.11   448.9  760.08   458.7  763.52
#Mann= 3 , 0 , 0
       0     .06       0   244.5    .045       0   273.5      .1       0
Bank Sta=244.5,273.5
XS Rating Curve= 0 ,0
Exp/Cntr=0.3,0.1

Type RM Length L Ch R = 1 ,4064.2  ,348.4,355,360.4
XS GIS Cut Line= 4
     1564915.799      351457.712     1564883.247      351291.697
     1564724.827      351144.127     1564588.108      351038.876
#Sta/Elev= 30
       0  762.78    28.2  752.12    65.8  737.34    75.2  734.28    84.6  732.68
      94  731.92   103.4  729.75   112.8  725.96   122.2  722.69   131.6  720.92
     141  720.29   198.7  717.84   287.3  712.58   316.8  710.89   326.6  711.31
   336.5  713.76   346.3  717.15   356.2  718.93     366   719.6   375.8  719.55
   404.8  717.87   414.4   717.7     424  718.43   433.6  721.14   443.2  724.89
   452.8  729.05   481.5  742.28   491.1  745.84   519.9   753.7   558.2  763.03
#Mann= 3 , 0 , 0
       0    .065       0   287.3    .045       0   336.5     .06       0
#XS Ineff= 2 , 0
                          363.31           728.5
Permanent Ineff=
       F       F
Bank Sta=287.3,336.5
XS Rating Curve= 0 ,0
Exp/Cntr=0.3,0.1

Type RM Length L Ch R = 1 ,3709.2  ,133.9,133.7,133.4
XS GIS Cut Line= 4
     1565209.853      351215.742     1565090.496      351079.023
     1564976.563      350911.923     1564888.673       350795.82
#Sta/Elev= 30
       0  754.93    38.2  739.42    66.9  728.07    76.4  724.45      86  721.55
    95.5  720.47   105.1  719.62   114.6  718.28   124.2  717.18   133.7  716.84
   210.4  716.61     220  716.07   229.6  713.91   237.8  711.06   239.3  710.54
   248.9  708.94   258.5  709.72   262.8  710.83   277.8  714.45   287.4  715.14
   335.6  715.32   354.8  715.52   374.1  716.08   393.4  716.88   403.2  717.36
   412.9  718.34   422.6  720.54   432.3  723.83   461.4  734.78   529.4  760.83
#Mann= 3 , 0 , 0
       0    .065       0   237.8    .045       0   262.8     .06       0
Bank Sta=237.8,262.8
XS Rating Curve= 0 ,0
Exp/Cntr=0.3,0.1

Type RM Length L Ch R = 1 ,3575.5  ,144.7,152.8,161.3
XS GIS Cut Line= 2
     1565307.411      351155.895     1564979.308      350684.112
#Sta/Elev= 30
       0  761.94    48.7   746.2    87.7  735.31    97.4  731.36   107.1  726.79
   116.9  723.13   136.4  720.22   155.8  715.47   165.6  714.33     224  713.39
   233.8  712.54   243.5   710.3   253.2  708.58     263  708.64   272.7  710.45
   282.5  712.87   292.2   713.6   331.2  712.94   350.6  713.23   409.1  717.87
   418.8   719.1   428.6  721.32     448  727.47     487  737.55   506.5  743.89
   516.2  747.76     526  752.26   555.2  769.18   564.9  773.99   574.7  777.52
#Mann= 3 , 0 , 0
       0    .065       0   243.5    .045       0   272.7     .06       0
#XS Ineff= 2 , 0
          200.14   721.6  340.37          721.73
Permanent Ineff=
       F       F
Bank Sta=243.5,272.7
XS Rating Curve= 0 ,0
Exp/Cntr=0.3,0.1