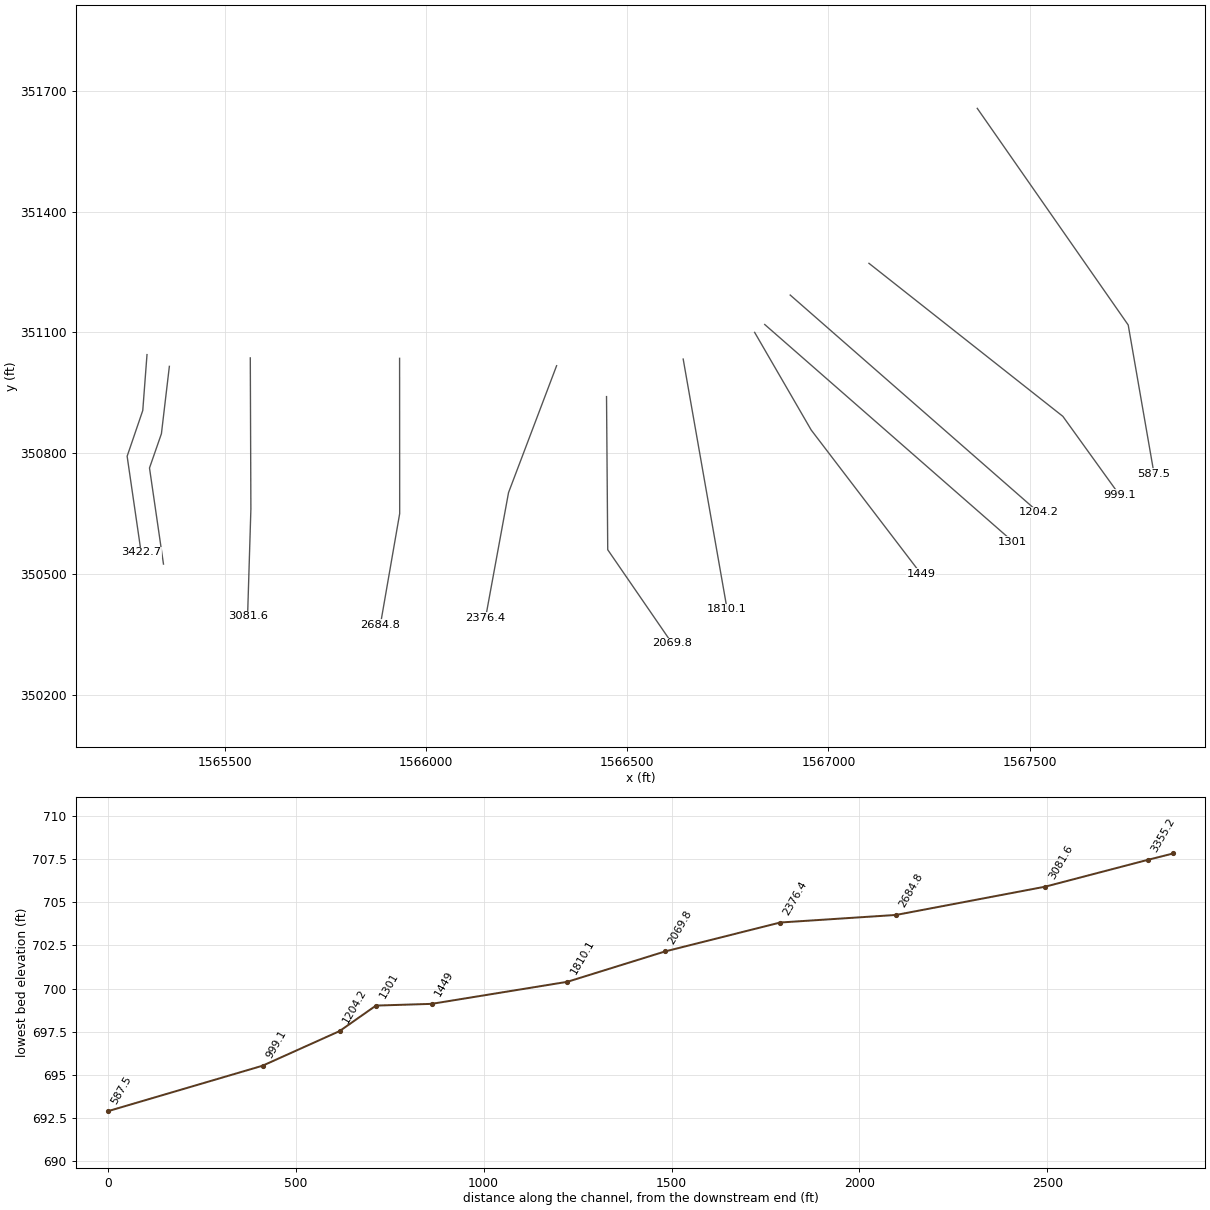
HEC-RAS study LSNCHOCRK.prj: LSNCHOCRK

--- LSNCHOCRK.g01 (geometry) --- (continued)

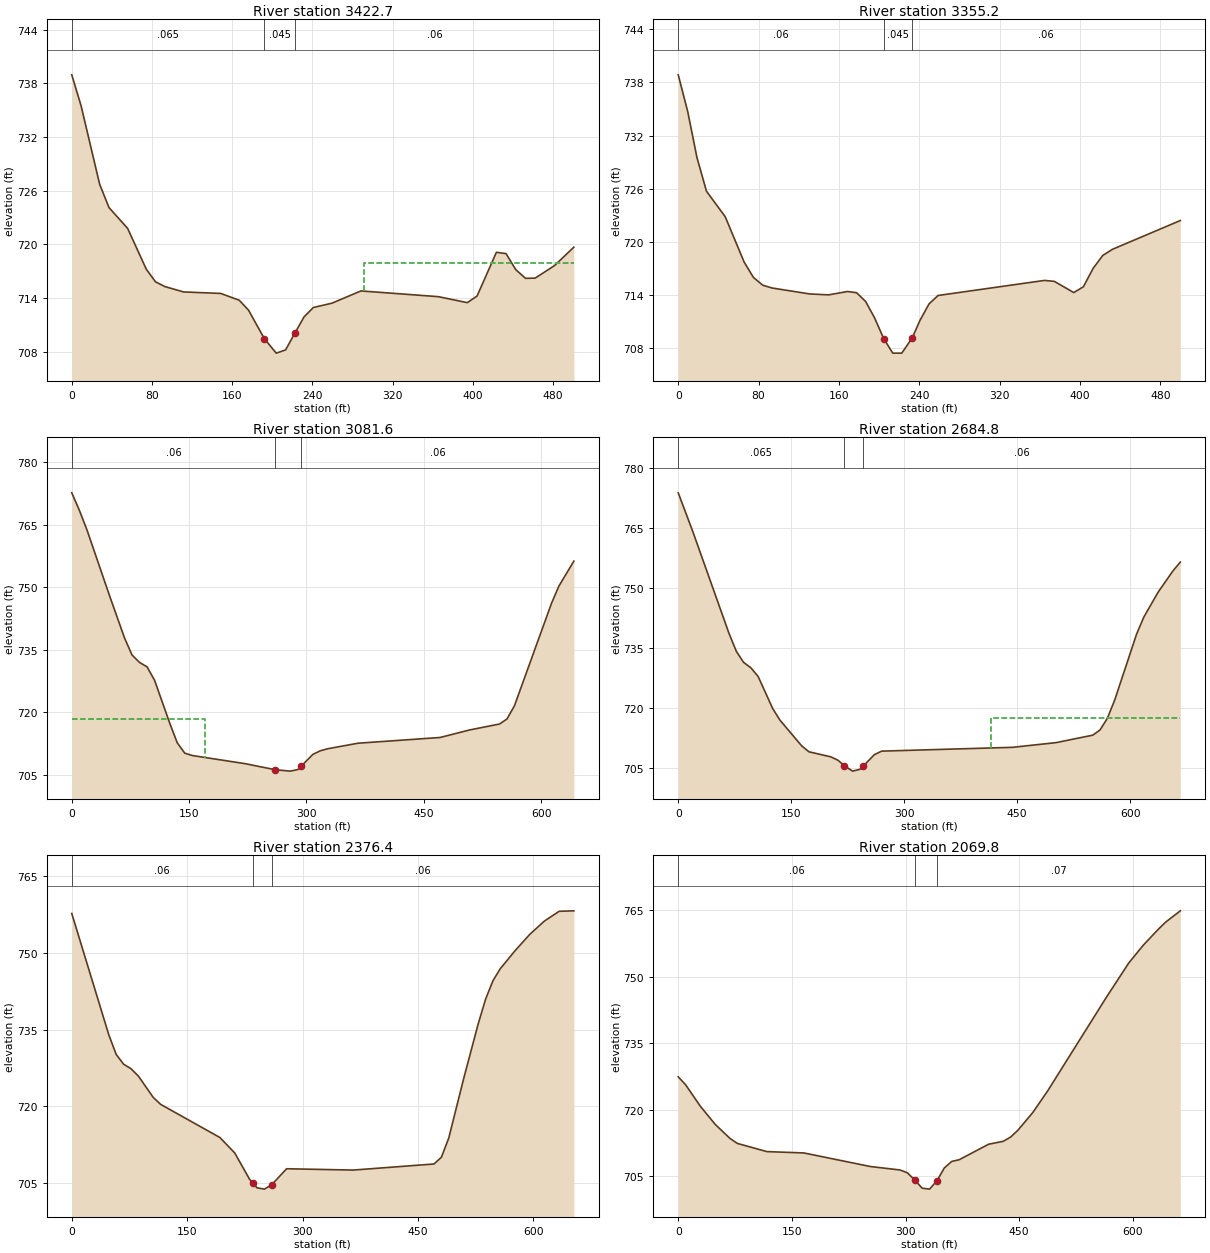
Type RM Length L Ch R = 1 ,3422.7  ,67.7,67.5,67.3
XS GIS Cut Line= 4
     1565306.925      351044.515     1565296.408      350905.681
     1565257.576      350791.998     1565292.298      350553.282
#Sta/Elev= 30
       0  738.94     9.3  735.48    27.8  726.71    37.1  724.11    55.7  721.78
    74.3  717.22    83.5  715.81    92.8  715.28   111.4  714.68   148.5  714.51
     167  713.75   176.2  712.65   192.1  709.44   203.9  707.84   213.2   708.2
   222.4  710.06   231.6  711.89   240.9  712.94   259.4  713.42   288.3  714.79
   365.5  714.15   394.4  713.48   404.1  714.22   423.4  719.11     433  718.96
   442.7  717.17   452.4   716.2     462  716.22   481.3  717.62   500.6  719.68
#Mann= 3 , 0 , 0
       0    .065       0   192.1    .045       0   222.4     .06       0
#XS Ineff= 2 , 0
                          291.08          717.89
Permanent Ineff=
       F       F
Bank Sta=192.1,222.4
XS Rating Curve= 0 ,0
Exp/Cntr=0.3,0.1

Type RM Length L Ch R = 1 ,3355.2  ,263.4,273.6,281.5
XS GIS Cut Line= 4
      1565362.48      351015.348     1565342.732      350847.944
     1565313.131      350762.831     1565347.853      350524.116
#Sta/Elev= 30
       0  738.85     9.4  734.73    18.7   729.5    28.1  725.73    46.8  722.85
    65.6  717.74    74.9     716    84.3  715.12    93.6  714.81   131.1  714.14
   149.8  714.04   168.6  714.42   177.6  714.28   186.6  713.29   195.6  711.42
   204.6   709.1   213.6  707.47   222.6  707.47     233   709.2   240.7  711.16
   249.7  713.02   258.7  713.97   364.8  715.67   374.5  715.56   393.8   714.3
   403.4  714.95   413.1  717.03   422.7  718.48   432.4  719.18   499.9  722.42
#Mann= 3 , 0 , 0
       0     .06       0   204.6    .045       0     233     .06       0
Bank Sta=204.6,233
XS Rating Curve= 0 ,0
Exp/Cntr=0.3,0.1

Type RM Length L Ch R = 1 ,3081.6  ,396.2,396.7,395.5
XS GIS Cut Line= 3
     1565563.542      351036.349     1565565.016      350660.777
     1565556.811      350394.627
#Sta/Elev= 30
       0   772.6     9.6  768.47    19.3  763.78    48.2     748    67.4  737.84
      77  733.75    86.7  731.95    96.3  730.89   105.9  727.66   125.2  717.42
   134.8  712.72   144.4  710.22   154.1  709.65   221.5   707.7     260  706.25
   279.3  705.91   288.9  706.27   293.2  707.08   308.2  709.92   317.8  710.79
   327.4  711.28     366   712.6   470.7  713.97   508.7  715.78   546.8   717.2
   556.3   718.4   565.8  721.53   613.3  746.15   622.8  750.29   641.8  756.23
#Mann= 3 , 0 , 0
       0     .06       0     260    .045       0   293.2     .06       0
#XS Ineff= 2 , 0
          170.54   718.4
Permanent Ineff=
       F       F
Bank Sta=260,293.2
XS Rating Curve= 0 ,0
Exp/Cntr=0.3,0.1

Type RM Length L Ch R = 1 ,2684.8  ,318.3,308.4,298.3
XS GIS Cut Line= 3
     1565934.446      351035.268      1565934.67       350649.46
     1565886.612      350372.727
#Sta/Elev= 30
       0  773.74    19.3   764.1    67.5  738.61    77.2  734.16    86.8  731.41
    96.4  730.08   106.1   727.9   125.4  719.91     135  717.02     164  710.56
   173.6  709.09   202.6  707.84   212.2  706.98   220.6  705.62   231.5  704.27
   241.1  704.71   245.6  705.51   260.4  708.37   270.1  709.26   443.9  710.21
     502  711.39   550.5  713.25   560.1  714.55   569.8  717.45   579.5  721.97
   608.6  738.45   618.3  742.74   637.6  749.05     657  754.27   666.7  756.45
#Mann= 3 , 0 , 0
       0    .065       0   220.6    .045       0   245.6     .06       0
#XS Ineff= 2 , 0
                          414.94           717.6
Permanent Ineff=
       F       F
Bank Sta=220.6,245.6
XS Rating Curve= 0 ,0
Exp/Cntr=0.3,0.1

Type RM Length L Ch R = 1 ,2376.4  ,294.7,306.6,317.1
XS GIS Cut Line= 3
     1566324.527      351016.913     1566205.108        350701.7
     1566148.114      350391.173
#Sta/Elev= 30
       0  757.66    48.2  733.94    57.8  730.13    67.4  728.23      77  727.35
    86.7  725.89   105.9  721.75   115.6  720.38   192.6  713.91   211.9  710.89
   231.1  705.78     235   705.1   240.8  704.09   250.4  703.83     260  704.68
   279.3  707.81   365.8  707.55     471  708.74   480.6  710.06   490.2  713.82
   509.3  725.27   528.4  736.08     538   740.9   547.6  744.52   557.1  746.87
   576.2  750.36   595.4  753.57   614.5  756.18   633.7  758.09   652.8  758.18
#Mann= 3 , 0 , 0
       0     .06       0     235    .045       0     260     .06       0
Bank Sta=235,260
XS Rating Curve= 0 ,0
Exp/Cntr=0.3,0.1

Type RM Length L Ch R = 1 ,2069.8  ,255.2,259.7,264.3
XS GIS Cut Line= 3
     1566448.548      350940.202     1566451.556      350559.732
     1566611.439      350327.154
#Sta/Elev= 30
       0  727.48     9.8  725.68    29.3  720.82    48.8  716.75    68.3  713.59
      78  712.46   117.1  710.61   165.8  710.31   253.6  707.25   292.7  706.47
   302.4  705.84   312.2   704.2     322  702.36   331.7  702.15   341.5  704.03
   351.2  706.92     361   708.4   370.7  708.77   409.7  712.28   429.1  712.94
   438.9  713.91   448.6  715.48   468.1  719.45   487.5  724.27   565.4  745.49
   594.6  753.14     614   757.2   633.5  760.73   643.2  762.35   662.7  764.92
#Mann= 3 , 0 , 0
       0     .06       0   312.2    .045       0   341.5     .07       0
Bank Sta=312.2,341.5
XS Rating Curve= 0 ,0
Exp/Cntr=0.3,0.1

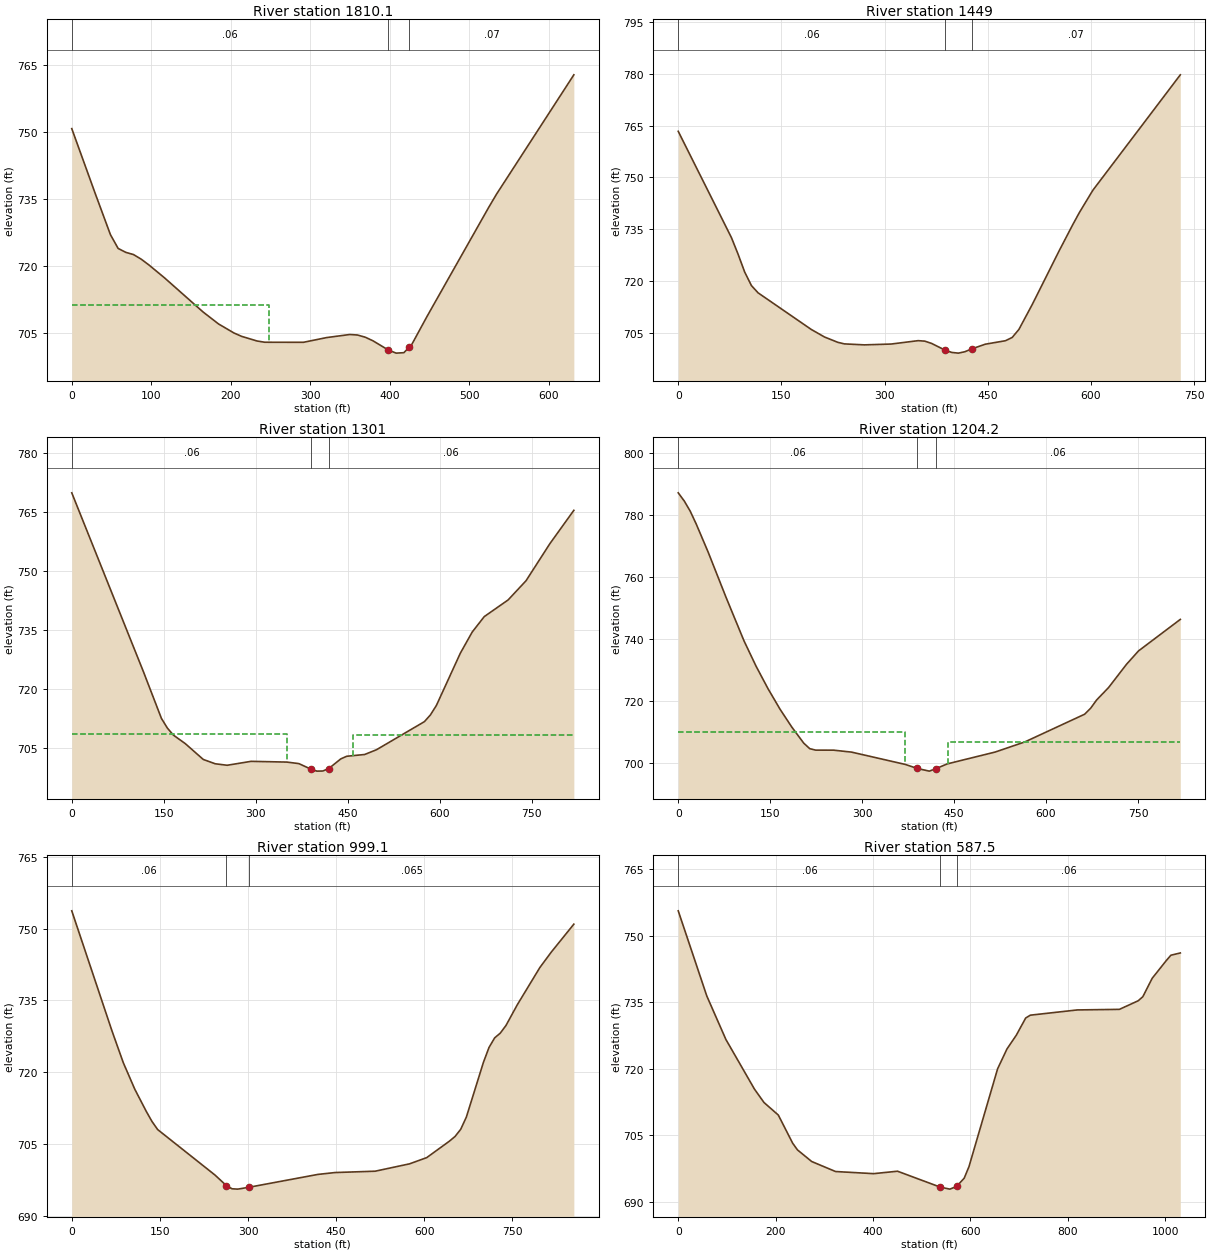
Type RM Length L Ch R = 1 ,1810.1  ,347.4,361.2,373.8
XS GIS Cut Line= 2
     1566639.001      351033.445     1566748.157      350411.789
#Sta/Elev= 30
       0  750.77    29.1   736.4    48.6  726.98    58.3  723.88      68     723
    77.7   722.5    87.4  721.46    97.1  720.16   116.5   717.3   165.1  709.62
   184.5  706.94   203.9  704.91   213.6  704.15     233  703.11   242.8  702.83
   291.3  702.82   320.4  703.88   349.6  704.57   359.3  704.45     369  703.96
   378.7  703.15   398.1  701.08   407.8  700.39   417.5  700.49   424.2  701.71
   427.2  702.25   446.7  708.65   524.4  733.17   534.1  736.09   631.2  762.84
#Mann= 3 , 0 , 0
       0     .06       0   398.1    .045       0   424.2     .07       0
#XS Ineff= 2 , 0
          248.37  711.08
Permanent Ineff=
       F       F
Bank Sta=398.1,424.2
XS Rating Curve= 0 ,0
Exp/Cntr=0.3,0.1

Type RM Length L Ch R = 1 ,1449    ,142.4,148,153.5
XS GIS Cut Line= 3
     1566816.517      351099.723     1566957.067      350857.108
     1567229.928       350499.68
#Sta/Elev= 30
       0  763.32    77.4  732.53      87  727.76    96.7  722.55   106.4  718.68
     116  716.58   193.4  705.97   212.7  703.78     232  702.24   241.7  701.78
   270.7   701.5   309.7  701.74   348.8  702.72   358.6  702.58   368.4  701.92
   387.9  699.99   397.7  699.31   407.5  699.11     417  699.53     427  700.35
   446.6   701.7   475.9   702.7   485.7  703.66   495.4  705.97     515  713.27
   554.1   728.8   573.6  736.26   583.4  739.83     603  746.28   730.1  779.67
#Mann= 3 , 0 , 0
       0     .06       0   387.9    .045       0     427     .07       0
Bank Sta=387.9,427
XS Rating Curve= 0 ,0
Exp/Cntr=0.3,0.1

Type RM Length L Ch R = 1 ,1301    ,96.8,96.8,96.8
XS GIS Cut Line= 3
     1566841.556      351119.327     1567149.748      350849.683
     1567457.941      350580.039
#Sta/Elev= 30
       0  769.79     117  724.25   146.2  712.44     156  709.95   165.8  708.17
   185.2     706   214.5  701.98     234  700.88   253.5   700.5   292.5   701.5
     351  701.31   370.5  700.92     390  699.52   399.8  699.01   409.5  699.04
   419.2  699.66   438.8  702.12   448.5  702.79   477.8  703.24   497.2  704.46
   575.2  711.59     585   713.3   594.8  715.72   633.8  728.99   653.2  734.38
   672.8   738.3   711.8  742.55     741  747.43     780  756.88     819  765.34
#Mann= 3 , 0 , 0
       0     .06       0     390    .045       0   419.2     .06       0
#XS Ineff= 2 , 0
          350.57   708.4  458.22          708.27
Permanent Ineff=
       F       F
Bank Sta=390,419.2
XS Rating Curve= 0 ,0
Exp/Cntr=0.3,0.1

Type RM Length L Ch R = 1 ,1204.2  ,203.6,205.1,206.4
XS GIS Cut Line= 3
     1566904.877      351192.485     1567213.069      350922.841
     1567521.262      350653.197
#Sta/Elev= 30
       0  787.13     9.8  784.51    19.5  781.24    29.2  777.15    48.8  768.05
      78  753.48   107.2  739.51   126.8  731.38   146.2  724.16   165.8  717.55
   185.2  711.73   204.8  706.52   214.5  704.77   224.2  704.29   253.5  704.28
   282.8  703.65   370.5  699.68     390  698.39   409.5  697.53   419.8  698.27
   438.8  699.86   516.8  703.66   565.5  706.94     663  715.86   672.8  717.79
   682.5  720.44     702  724.44   731.2  731.91   750.8  736.23     819  746.38
#Mann= 3 , 0 , 0
       0     .06       0     390    .045       0   419.8     .06       0
#XS Ineff= 2 , 0
           370.4     710  440.51             707
Permanent Ineff=
       F       F
Bank Sta=390,419.8
XS Rating Curve= 0 ,0
Exp/Cntr=0.3,0.1

Type RM Length L Ch R = 1 ,999.1   ,419,411.7,402.8
XS GIS Cut Line= 3
     1567100.515      351271.309     1567582.286      350891.101
     1567722.911      350695.788
#Sta/Elev= 30
       0  753.75    68.2  728.71    87.7  721.97   107.2  716.44   126.6  711.83
   136.4   709.7   146.1  707.99   243.5  698.49     263  696.27   272.8  695.59
   282.5  695.52     302  695.92   418.9   698.6   448.1  698.99   516.3  699.27
   574.8  700.81     604  702.11   642.6  705.55   652.2  706.53   661.9  708.04
   671.5   710.6   700.4     722     710  725.15   719.6  727.16   729.2  728.16
   738.9  729.76   758.1  734.08   796.6  741.89   815.9   745.1   854.4  750.96
#Mann= 3 , 0 , 0
       0     .06       0     263    .045       0     302    .065       0
Bank Sta=263,302
XS Rating Curve= 0 ,0
Exp/Cntr=0.3,0.1

Type RM Length L Ch R = 1 ,587.5   ,570.3,587.5,580.7
XS GIS Cut Line= 3
     1567369.613      351656.292     1567744.613      351118.097
     1567808.849      350748.305
#Sta/Elev= 30
       0  755.64    58.7  736.43    97.9  726.63   156.6  715.43   176.2  712.41
   205.6  709.58     235  703.25   244.8  701.74   274.1  699.11   323.1  696.85
   401.4  696.37   450.4  696.92   538.5  693.32     558  692.88   571.8  693.49
   587.4  695.35   597.2  697.95     656  720.01   675.2  724.48   694.4  727.59
   713.7  731.47   723.3  732.11   819.6  733.29   906.2  733.42   944.7  735.35
   954.3  736.27   973.5  740.42  1002.4  744.41    1012  745.63  1031.3  746.14
#Mann= 3 , 0 , 0
       0     .06       0   538.5    .045       0   571.8     .06       0
Bank Sta=538.5,571.8
XS Rating Curve= 0 ,0
Exp/Cntr=0.3,0.1

Chan Stop Cuts=-1
Use User Specified Reach Order=0
Composite Channel Slope=5